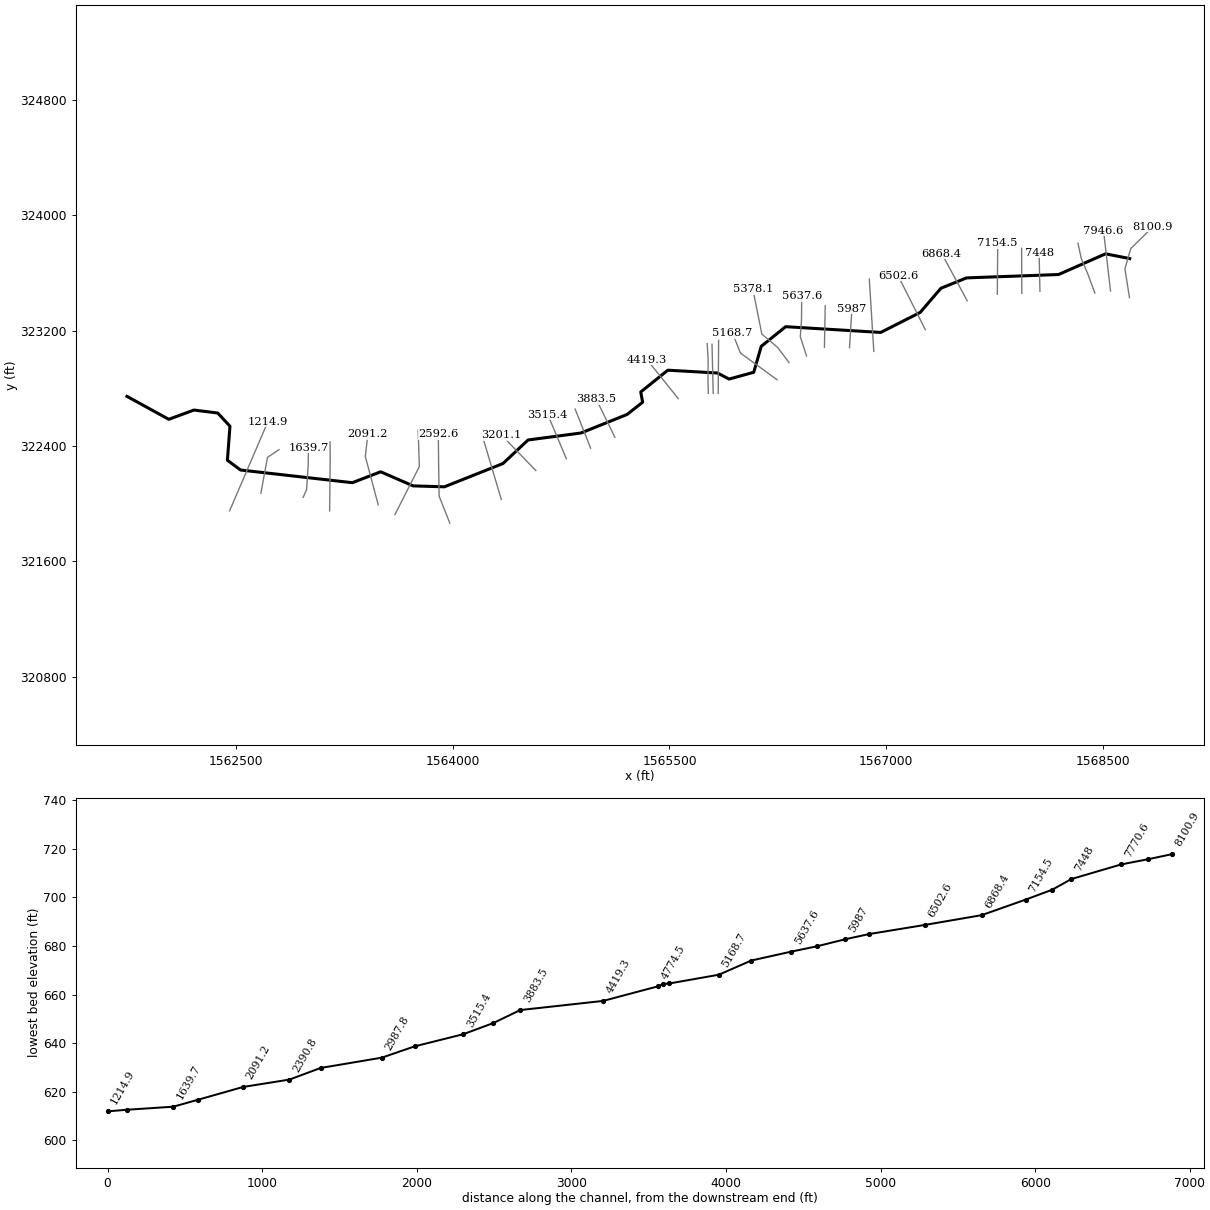
--- STHSTNCLCR.prj (project) ---

Proj Title=STHSTNCLCR
Current Plan=p01
Default Exp/Contr=0,0
English Units
Geom File=g01
Flow File=f01
Plan File=p01
BEGIN DESCRIPTION:
END DESCRIPTION:
DSS Export Rating Curves= 0
DSS Export Rating Curve Sorted= 0
DSS Export Volume Flow Curves= 0
DXF OffsetX= 0
DXF OffsetY= 0
DXF ScaleX= 0
DXF ScaleY= 0

--- STHSTNCLCR.p01 (plan) ---

Plan Title=Floodplain
Program Version=4.00
Geom File=g01
Flow File=f01
K Sum by GR=0
Std Step Tol=0.01
Critical Tol=0.01
Num of Std Step Trials=20
Max Error Tol=0.3
Flow Tol Ratio=0.001
Split Flow NTrial=30
Split Flow Tol=0.02
Split Flow Ratio=0.02
Log Output Level=0
Friction Slope Method=1
Unsteady Friction Slope Method=2
Unsteady Bridges Friction Slope Method=1
Global Log Level=0
CheckData=False
Run HTab=0
Run UNet=0
Run PostProcess=0
UNET Theta=0
UNET Theta Warmup=0
UNET ZTol=0
UNET ZSATol=0
UNET MxIter=0
UNET MaxInSteps=0
UNET DtIC=0
UNET DtMin=0
UNET MaxCRTS=0
UNET WFStab=0
UNET SFStab=0
UNET WFX=0
UNET SFX=0
UNET DSS MLevel=0
UNET DZMax Abort=0
UNET Convert EG Bridges=0
UNET Use Existing IB Tables=0
UNET Froude Limit=0
UNET Froude Power=0
Write IC File=0
Echo Input=False
Echo Output=False
Write Detailed=0

--- STHSTNCLCR.f01 (steady flow) ---

Flow Title=NFF Regression Equation
Program Version=4.00
Number of Profiles= 1
Profile Names=P100yr
River Rch & RM=STHSTNCLCR,Main            ,8100.9
349.6545
River Rch & RM=STHSTNCLCR,Main            ,7770.6
352.3306
River Rch & RM=STHSTNCLCR,Main            ,6868.4
 389.126
River Rch & RM=STHSTNCLCR,Main            ,5987
419.7665
River Rch & RM=STHSTNCLCR,Main            ,5378.1
457.0572
River Rch & RM=STHSTNCLCR,Main            ,2592.6
505.2688
River Rch & RM=STHSTNCLCR,Main            ,2390.8
657.0581
Boundary for River Rch & Prof#=STHSTNCLCR,Main            , 1
Up Type= 0
Dn Type= 3
Dn Slope=0.00504
DSS Import GetInterval= 0
DSS Import GetPeak= 0
DSS Import FillOption= 0

--- STHSTNCLCR.g01 (geometry) ---

Geom Title=Geometry
Program Version=4.00

River Reach=STHSTNCLCR      ,Main
Reach XY= 30
     1568685.871      323699.232     1568518.556      323732.258
     1568193.176      323588.594     1567556.232       323565.29
     1567378.924      323493.346     1567235.359      323325.844
     1566962.201       323187.18     1566303.845      323227.016
     1566135.144      323090.789     1566083.128      322910.865
     1565912.234      322863.743     1565832.781       322905.72
     1565488.545      322925.373     1565300.888      322774.296
     1565314.094      322703.402     1565206.843      322618.695
     1564886.927      322489.762     1564520.949      322441.503
     1564346.936      322278.139     1563941.691      322116.685
     1563725.094      322123.136     1563500.637      322220.916
     1563304.137       322145.26     1562530.588      322233.179
     1562439.528      322300.922     1562457.095      322536.855
     1562372.591      322628.308     1562207.701      322648.944
     1562033.587      322584.862     1561744.164      322743.901

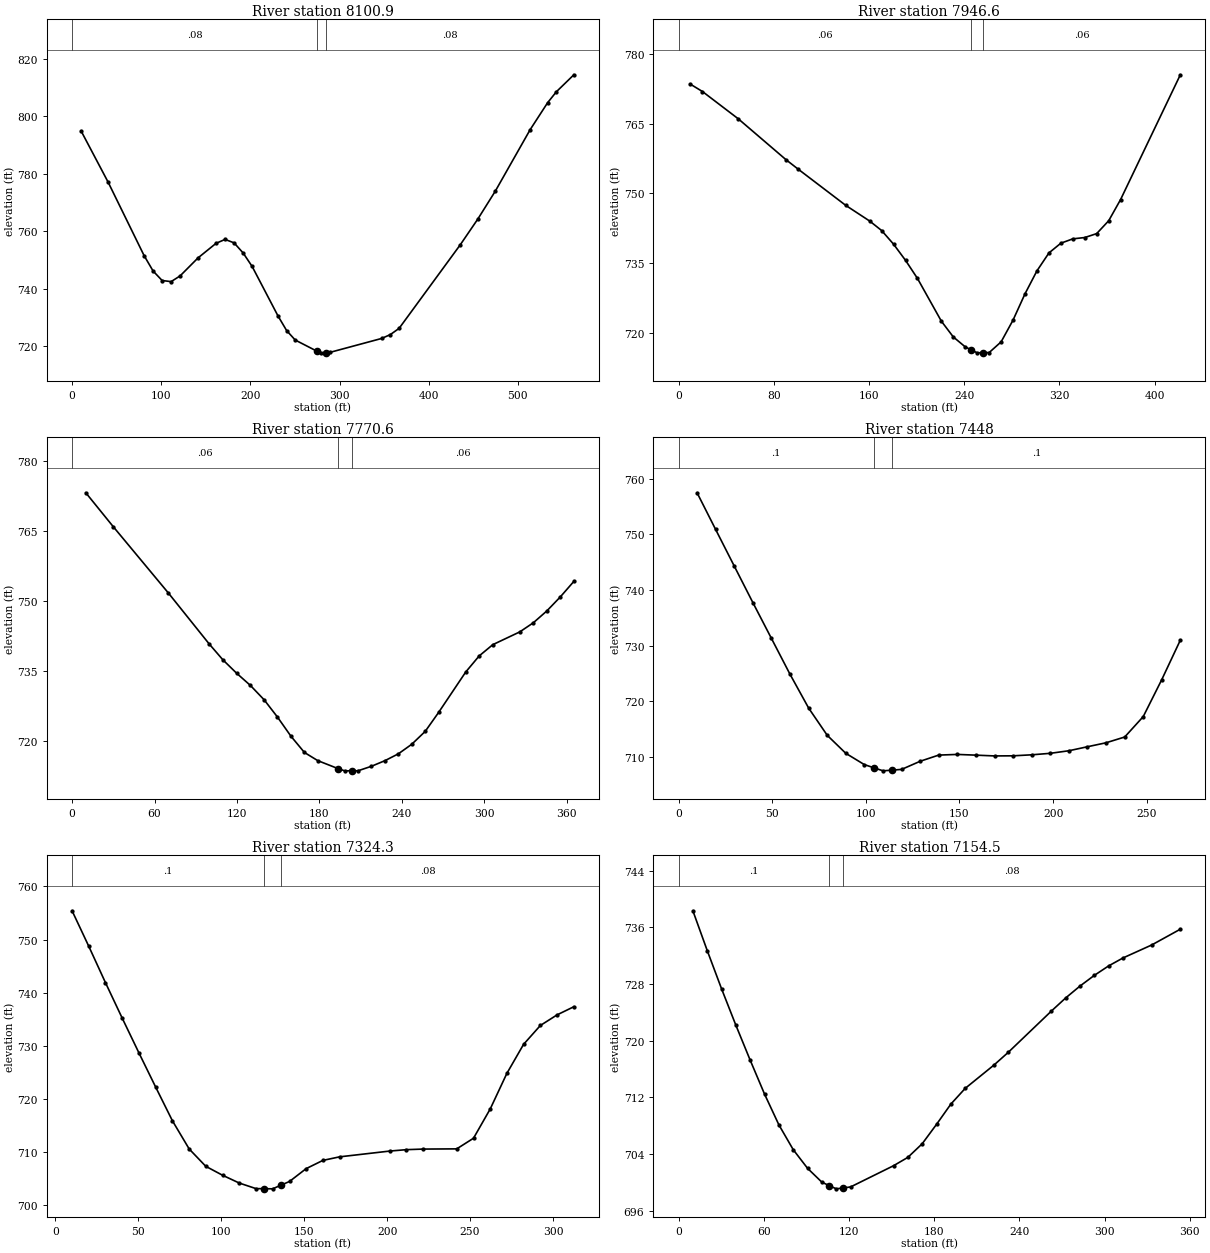
Type RM Length L Ch R = 1 ,8100.9  ,146.4,154.3,162.2
XS GIS Cut Line= 4
     1568684.154      323428.884     1568652.807      323628.364
     1568692.703         323768.     1568846.588      323919.035
#Sta/Elev= 30
    10.1  794.93    40.4  777.14    80.8  751.57    90.9  746.21     101  742.92
   111.1  742.53   121.2  744.53   141.3  750.79   161.5  755.85   171.6  757.21
   181.7  756.01   191.8  752.52   201.9  747.84     231  730.58   240.7  725.49
   250.3  722.22   274.4  718.38   279.4  717.77   284.4  717.85   289.1  717.92
   347.2  722.77     357  724.12   366.8  726.28   435.4  755.34     455  764.25
   474.6  773.94   513.8  795.38   533.4  804.75   543.2  808.55   562.8  814.45
#Mann= 3 , 0 , 0
       0     .08       0   274.4    .045       0   284.4     .08       0
Bank Sta=274.4,284.4
XS Rating Curve= 0 ,0
Exp/Cntr=0.3,0.1

Type RM Length L Ch R = 1 ,7946.6  ,170.2,176,181.7
XS GIS Cut Line= 2
     1568553.067       323474.48     1568504.622      323893.388
#Sta/Elev= 30
      10  773.46    20.1  771.89    50.2  766.02    90.4  757.21   100.4  755.22
   140.6  747.39   160.6  744.04   170.7  741.99   180.7  739.06   190.8  735.57
   200.8  731.69   220.9  722.49   230.9  719.11     241  716.96     246  716.32
     251  715.69     256  715.73   261.1  715.76   271.1  718.05   281.1  722.72
   291.2   728.4   301.2  733.32   311.3  737.18   321.3  739.27   331.3   740.2
   341.4  740.49   351.4  741.33   361.5   744.1   371.5  748.66   421.7  775.49
#Mann= 3 , 0 , 0
       0     .06       0     246    .045       0     256     .06       0
Bank Sta=246,256
XS Rating Curve= 0 ,0
Exp/Cntr=0.3,0.1

Type RM Length L Ch R = 1 ,7770.6  ,330.3,322.6,314.9
XS GIS Cut Line= 4
     1568444.778      323460.231     1568396.333      323591.318
     1568350.631      323699.294      1568327.94      323805.046
#Sta/Elev= 30
      10  773.11    29.9  765.87    69.9   751.7    99.8  740.71   109.8   737.3
   119.8  734.43   129.8  731.82   139.8  728.74   149.5  725.04   159.3  720.94
   169.1  717.46   178.8  715.71   193.4  714.02   198.4  713.52   203.4  713.53
   208.1  713.53   217.9   714.5   227.7   715.7   237.5  717.17   247.2  719.21
     257  721.97   266.8  726.05   286.5   734.7   296.3  738.15   306.2  740.56
   325.8  743.29   335.7  745.25   345.5  747.78   355.3  750.78   365.2  754.12
#Mann= 3 , 0 , 0
       0     .06       0   193.4    .045       0   203.4     .06       0
Bank Sta=193.4,203.4
XS Rating Curve= 0 ,0
Exp/Cntr=0.3,0.1

Type RM Length L Ch R = 1 ,7448    ,124.1,123.8,123.4
XS GIS Cut Line= 2
     1568064.489      323473.026     1568058.789      323740.899
#Sta/Elev= 29
     9.9  757.48    19.8  750.89    29.8  744.27    39.7  737.73    49.6   731.3
    59.5  724.87    69.5  718.76    79.4  713.88    89.3  710.65    99.2  708.62
   104.2  708.06   109.2   707.5   114.2  707.63   119.1  707.76     129  709.22
   138.9  710.33   148.9  710.45   158.8  710.32   168.7  710.18   178.6   710.2
   188.5  710.38   198.5  710.65   208.4  711.11   218.3  711.83   228.2  712.54
   238.2  713.58   248.1  717.25     258   723.9   267.9  730.99
#Mann= 3 , 0 , 0
       0      .1       0   104.2    .045       0   114.2      .1       0
Bank Sta=104.2,114.2
XS Rating Curve= 0 ,0
Exp/Cntr=0.3,0.1

Type RM Length L Ch R = 1 ,7324.3  ,170,169.8,169.5
XS GIS Cut Line= 2
     1567938.986      323457.889     1567937.591       323770.46
#Sta/Elev= 30
    10.1  755.42    20.2  748.72    30.2  741.92    40.3  735.24    50.4  728.69
    60.5  722.25    70.6  715.91    80.7  710.61    90.7  707.35   100.8  705.67
   110.9   704.2     121  703.15   126.1  703.14     131  703.11   136.1  703.81
   141.2   704.5   151.2  706.91   161.3  708.46   171.4  709.13   201.7  710.22
   211.7  710.48   221.8  710.59     242  710.63   252.1  712.63   262.2  718.15
   272.2  724.82   282.3   730.3   292.4  733.84   302.5  735.84   312.6  737.37
#Mann= 3 , 0 , 0
    10.1      .1       0   126.1    .045       0   136.1     .08       0
Bank Sta=126.1,136.1
XS Rating Curve= 0 ,0
Exp/Cntr=0.3,0.1

Type RM Length L Ch R = 1 ,7154.5  ,275.9,286.1,296.5
XS GIS Cut Line= 2
     1567769.396      323451.682     1567772.246      323805.046
#Sta/Elev= 30
    10.1  738.33    20.2  732.72    30.3  727.32    40.4  722.17    50.5  717.23
    60.6  712.45    70.7  708.11    80.8  704.61    90.9  701.98     101  700.02
   106.1  699.55   111.1  699.09   116.1  699.22   121.2  699.36   151.4  702.35
   161.5  703.53   171.6  705.45   181.7  708.19   191.8  711.05   201.9  713.27
   222.1  716.55   232.2  718.35   262.5  724.16   272.6  726.02   282.7   727.7
   292.8  729.21   302.9  730.55     313  731.67   333.2   733.5   353.4  735.73
#Mann= 3 , 0 , 0
       0      .1       0   106.1    .045       0   116.1     .08       0
Bank Sta=106.1,116.1
XS Rating Curve= 0 ,0
Exp/Cntr=0.3,0.1

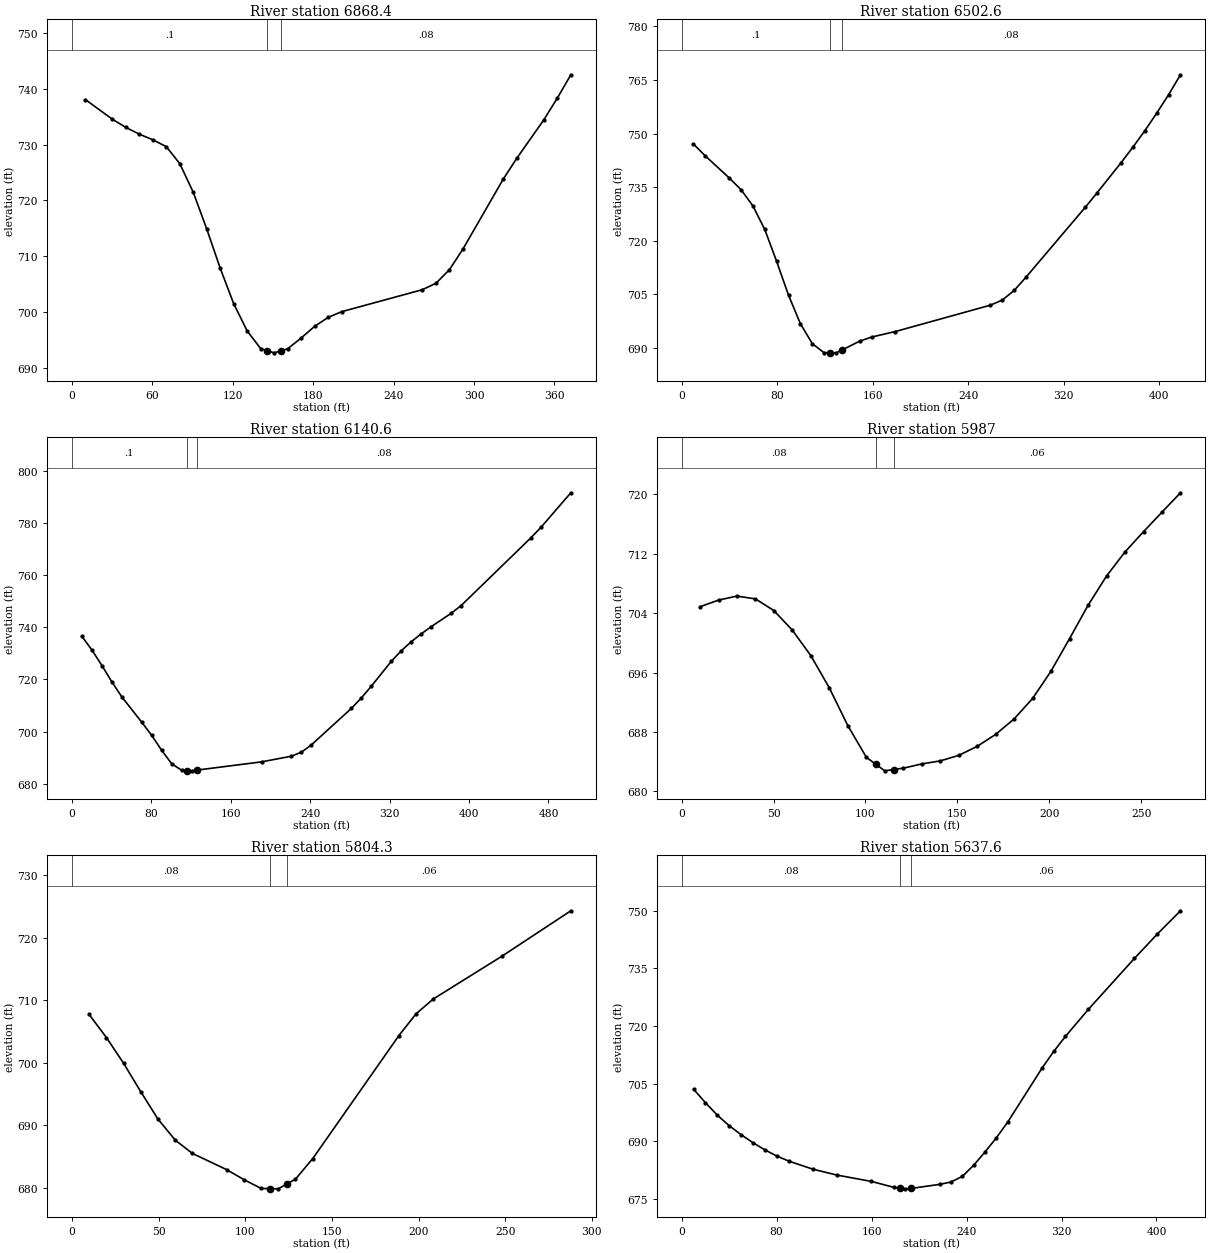
Type RM Length L Ch R = 1 ,6868.4  ,366.3,365.8,365.2
XS GIS Cut Line= 2
     1567561.367      323406.087     1567384.685      323733.804
#Sta/Elev= 30
    10.1  738.09    30.2  734.57    40.2  733.11    50.3  731.89    60.4  730.88
    70.4  729.66    80.5   726.6    90.6  721.43   100.6  714.88   110.7  707.81
   120.7  701.48   130.8  696.56   140.9   693.4   145.9  693.03   150.9  692.65
   155.9  693.01     161  693.38   171.1  695.32   181.1   697.4   191.2  699.01
   201.2  700.03   261.6  703.99   271.7  705.14   281.7  707.57   291.8  711.28
     322  723.88   332.1  727.61   352.2  734.48   362.2  738.36   372.3  742.55
#Mann= 3 , 0 , 0
       0      .1       0   145.9    .045       0   155.9     .08       0
Bank Sta=145.9,155.9
XS Rating Curve= 0 ,0
Exp/Cntr=0.3,0.1

Type RM Length L Ch R = 1 ,6502.6  ,370.2,362.1,361.7
XS GIS Cut Line= 2
     1567270.697      323206.607     1567082.616      323579.919
#Sta/Elev= 29
      10  747.05    19.9  743.74    39.8  737.61    49.8  734.31    59.7  729.79
    69.7  723.17    79.6  714.28    89.6  704.79    99.5  696.84   109.5  691.24
   119.4  688.68   124.4  688.67   129.4  688.65   134.4  689.43   149.3  691.93
   159.2  693.06   179.1  694.61   258.8  701.99   268.7  703.41   278.7  706.11
   288.6  709.82   338.4  729.42   348.3  733.48   368.3  741.87   378.2  746.21
   388.2  750.81   398.1  755.69   408.1  760.89     418  766.43
#Mann= 3 , 0 , 0
       0      .1       0   124.4    .045       0   134.4     .08       0
Bank Sta=124.4,134.4
XS Rating Curve= 0 ,0
Exp/Cntr=0.3,0.1

Type RM Length L Ch R = 1 ,6140.6  ,156,153.5,151
XS GIS Cut Line= 2
     1566914.483      323055.572     1566883.136      323557.122
#Sta/Elev= 30
    10.1  736.57    20.1  731.36    30.2  725.37    40.2   719.1    50.3  713.29
    70.4  703.54    80.4  698.48    90.5  692.71   100.5   687.6   110.6  685.09
   115.6  684.98   120.6  684.88   125.6  685.15     191  688.33   221.1  690.51
   231.2  692.07   241.2  694.86   281.4  708.87   291.5  712.91   301.5   717.4
   321.6  726.95   331.7  731.05   341.7   734.5   351.8  737.54   361.8   740.3
   381.9  745.42     392  748.42   462.3  774.49   472.4   778.5   502.5  791.79
#Mann= 3 , 0 , 0
       0      .1       0   115.6    .045       0   125.6     .08       0
Bank Sta=115.6,125.6
XS Rating Curve= 0 ,0
Exp/Cntr=0.3,0.1

Type RM Length L Ch R = 1 ,5987    ,181.6,182.8,183.9
XS GIS Cut Line= 2
     1566746.055      323081.219     1566763.153      323351.942
#Sta/Elev= 29
      10  704.85    20.1  705.75    30.1  706.29    40.2  705.91    50.2  704.34
    60.3  701.68    70.3  698.27    80.4  693.91    90.4  688.85   100.5  684.58
   105.5  683.67   110.5  682.76   115.5  682.94   120.6  683.12   130.6  683.69
   140.7   684.1   150.7  684.84   160.7  686.05   170.8  687.67   180.8  689.74
   190.9  692.51   200.9  696.18     211  700.57     221  705.03   231.1  708.99
   241.1  712.22   251.2  714.96   261.2  717.58   271.3   720.2
#Mann= 3 , 0 , 0
       0     .08       0   105.5    .045       0   115.5     .06       0
Bank Sta=105.5,115.5
XS Rating Curve= 0 ,0
Exp/Cntr=0.3,0.1

Type RM Length L Ch R = 1 ,5804.3  ,167.7,166.7,165.7
XS GIS Cut Line= 2
     1566572.517      323084.069     1566578.217       323371.89
#Sta/Elev= 20
     9.9  707.76    19.9  704.07    29.8  699.96    39.7  695.41    49.6  691.04
    59.6  687.66    69.5  685.53    89.3  682.93    99.3  681.33   109.2  679.92
   114.1  679.89   119.1  679.86   124.1  680.65     129  681.41     139  684.71
   188.6  704.35   198.5  707.84   208.5  710.23   248.2  717.09   287.9  724.35
#Mann= 3 , 0 , 0
       0     .08       0   114.1    .045       0   124.1     .06       0
Bank Sta=114.1,124.1
XS Rating Curve= 0 ,0
Exp/Cntr=0.3,0.1

Type RM Length L Ch R = 1 ,5637.6  ,240.4,259.5,278.5
XS GIS Cut Line= 4
     1566448.691      323023.917     1566405.433      323157.876
     1566413.805        323272.3     1566415.201      323436.958
#Sta/Elev= 30
    10.1   703.6    20.1  700.08    30.2  696.81    40.2  694.07    50.3  691.73
    60.3  689.63    70.4  687.76    80.4  686.17    90.5  684.85   110.6  682.78
   130.7  681.25   159.9  679.59     179  678.03   183.6  677.85   188.6  677.66
   193.6  677.78   217.3  678.82   226.8  679.42   236.4  680.88   245.9  683.76
   255.5  687.23   265.2  690.97   274.9  695.13   303.9  709.22   313.6  713.47
   323.3  717.32   342.7  724.39   381.4  737.62   400.8     744   420.2  750.02
#Mann= 3 , 0 , 0
       0     .08       0   183.6    .045       0   193.6     .06       0
Bank Sta=183.6,193.6
XS Rating Curve= 0 ,0
Exp/Cntr=0.3,0.1

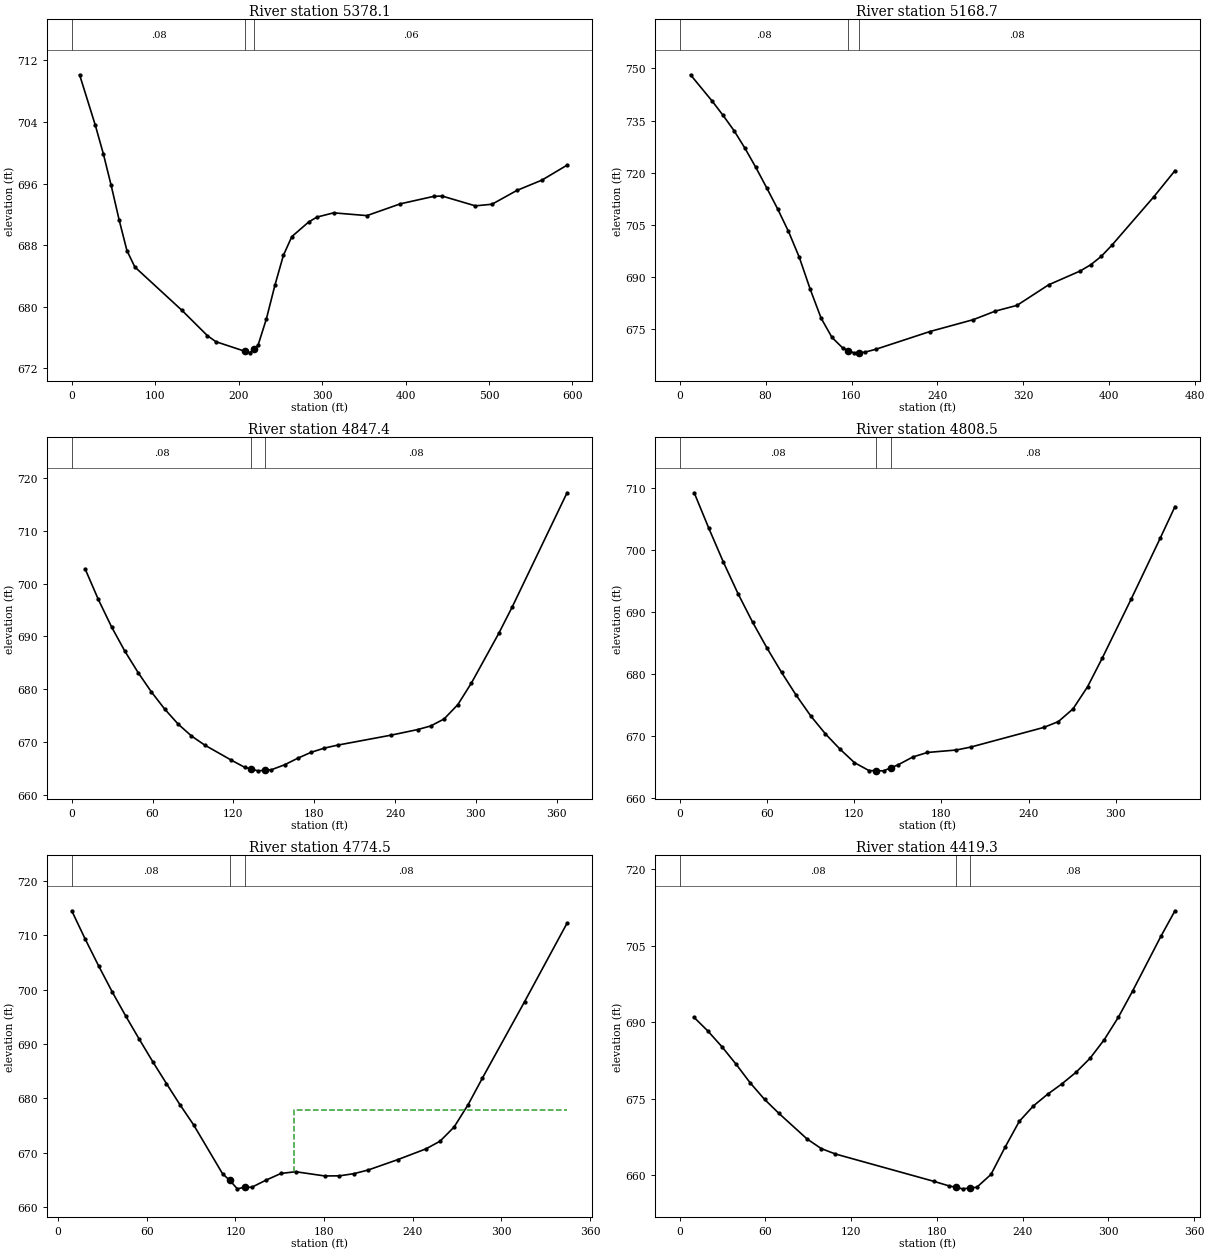
Type RM Length L Ch R = 1 ,5378.1  ,207.8,209.4,211.1
XS GIS Cut Line= 4
     1566327.442       322978.63      1566247.65      323084.069
     1566139.361       323175.26     1566076.667      323488.728
#Sta/Elev= 30
     9.4  710.14    28.3  703.56    37.8  699.89    47.2  695.78    56.7  691.31
    66.1  687.29    75.6  685.15   132.2   679.5   162.6  676.22   172.7  675.44
   208.1  674.17   213.1  673.99   218.1  674.47   223.2  674.96   233.3  678.43
   243.5   682.8   253.6  686.66   263.7   689.1   283.8  690.99   293.8  691.64
   313.8  692.19   353.7  691.83   393.7  693.36   433.6  694.33   443.6  694.38
   483.6   693.1   503.6  693.31   533.5  695.11   563.5  696.45   593.5  698.39
#Mann= 3 , 0 , 0
       0     .08       0   208.1    .045       0   218.1     .06       0
Bank Sta=208.1,218.1
XS Rating Curve= 0 ,0
Exp/Cntr=0.3,0.1

Type RM Length L Ch R = 1 ,5168.7  ,340.1,321.2,302.4
XS GIS Cut Line= 3
       1566244.8      322858.942     1565991.176      323044.173
     1565937.031       323180.96
#Sta/Elev= 30
    10.1  748.18    30.4  740.55    40.5  736.46    50.7  732.07    60.8  727.03
    70.9  721.53      81  715.66    91.2  709.59   101.3  703.11   111.4  695.64
   121.6  686.42   131.7  678.13   141.8   672.6     152  669.49   157.1  668.82
   162.1  668.15   167.1  668.23   172.2  668.32   182.4  669.15     233  674.28
   273.5  677.71   293.8  680.15   314.1  681.81   343.5  687.72   372.9   691.7
   382.7  693.49   392.5   695.9   402.3  699.07   441.6   713.1   461.2  720.59
#Mann= 3 , 0 , 0
       0     .08       0   157.1    .045       0   167.1     .08       0
Bank Sta=157.1,167.1
XS Rating Curve= 0 ,0
Exp/Cntr=0.3,0.1

Type RM Length L Ch R = 1 ,4847.4  ,38.5,38.9,39.3
XS GIS Cut Line= 2
     1565837.291      322764.902     1565840.141      323132.514
#Sta/Elev= 30
     9.9   702.8    19.7  697.02    29.6  691.78    39.5  687.17    49.4   683.1
    59.2  679.46    69.1  676.21      79  673.39    88.9  671.14    98.7  669.42
   118.5  666.56   128.3  665.22   133.2  664.88   138.2  664.54   143.2  664.64
   148.1  664.74     158  665.68   167.8  666.93   177.7  668.05   187.6  668.85
   197.4  669.41   236.9  671.29   256.7  672.35   266.5  673.04   276.4  674.36
   286.6  677.07   296.7  681.17     317  690.57   327.1  695.63   367.7   717.2
#Mann= 3 , 0 , 0
       0     .08       0   133.2    .045       0   143.2     .08       0
Bank Sta=133.2,143.2
XS Rating Curve= 0 ,0
Exp/Cntr=0.3,0.1

Type RM Length L Ch R = 1 ,4808.5  ,34.7,34,33.2
XS GIS Cut Line= 2
     1565802.617      322764.371     1565794.245      323104.851
#Sta/Elev= 29
      10  709.16      20  703.46    30.1  697.96    40.1  692.91    50.1  688.32
    60.1  684.11    70.1  680.19    80.1  676.53    90.2  673.16   100.2   670.3
   110.2  667.84   120.2  665.65   130.2  664.37   135.2  664.35   140.2  664.33
   145.2  664.82   150.3  665.31   160.3  666.56   170.3  667.29   190.3  667.69
   200.3  668.17   250.4  671.33   260.4  672.27   270.5  674.32   280.5  677.89
   290.5  682.46   310.5  692.03   330.6  701.91   340.6  706.93
#Mann= 3 , 0 , 0
       0     .08       0   135.2    .045       0   145.2     .08       0
Bank Sta=135.2,145.2
XS Rating Curve= 0 ,0
Exp/Cntr=0.3,0.1

Type RM Length L Ch R = 1 ,4774.5  ,341.7,355.3,369
XS GIS Cut Line= 4
     1565768.898      322764.902     1565766.336      322856.468
     1565767.732      322994.614     1565760.755      323109.037
#Sta/Elev= 30
     9.2  714.51    18.3  709.31    27.5  704.32    36.6  699.59    45.8  695.12
      55  690.84    64.1  686.72    73.3  682.73    82.4  678.86    91.6  675.17
   111.3  666.13   116.2  664.91  121.28  663.37   126.2  663.67   131.1  663.67
   140.9     665   150.8   666.2   160.7  666.52   180.4  665.74   190.3  665.76
   200.2  666.16     210  666.85   229.8  668.74   248.9  670.72   258.4  672.12
     268  674.75   277.5  678.88   287.1  683.73   315.7  697.81   344.4  712.23
#Mann= 3 , 0 , 0
     9.2     .08       0   116.2    .045       0   126.2     .08       0
#XS Ineff= 2 , 0
                          159.69          677.81
Permanent Ineff=
       F       F
Bank Sta=116.2,126.2
XS Rating Curve= 0 ,0
Exp/Cntr=0.3,0.1

Type RM Length L Ch R = 1 ,4419.3  ,539.5,535.7,531.4
XS GIS Cut Line= 2
     1565560.869      322727.855     1565344.291      322998.578
#Sta/Elev= 29
     9.9  691.02    19.8  688.28    29.7  685.18    39.6  681.75    49.5  678.09
    59.4  674.91    69.3   672.2    89.1  667.16    99.1  665.26     109   664.2
   178.3  658.81   188.2  657.97   193.1  657.68   198.1  657.37   203.1  657.53
     208  657.68   217.9  660.19   227.8  665.54   237.7  670.59   247.6  673.62
   257.5   675.9   267.4  677.91   277.4   680.2   287.3  682.97   297.2   686.6
   307.1  691.01     317  696.11   336.8  706.83   346.7  711.86
#Mann= 3 , 0 , 0
       0     .08       0   193.1    .045       0   203.1     .08       0
Bank Sta=193.1,203.1
XS Rating Curve= 0 ,0
Exp/Cntr=0.3,0.1

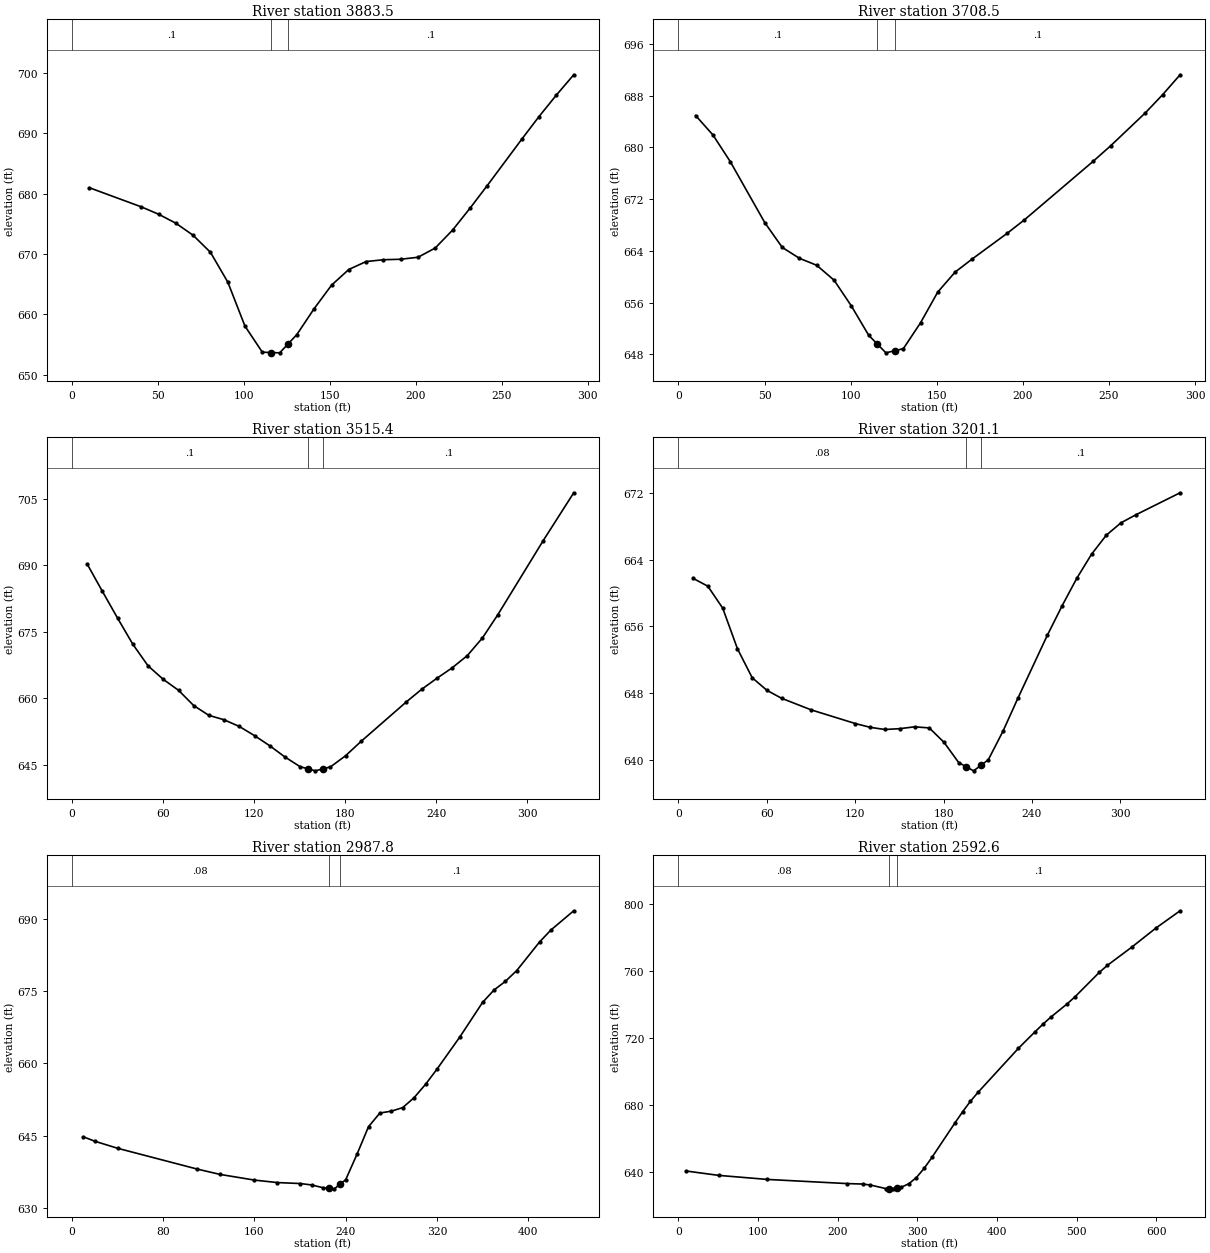
Type RM Length L Ch R = 1 ,3883.5  ,176.6,175.1,173.5
XS GIS Cut Line= 2
     1565122.014      322459.982     1564993.777      322722.156
#Sta/Elev= 28
    10.1  680.97    40.3   677.8    50.3  676.59    60.4  675.09    70.4   673.1
    80.5  670.28    90.6  665.34   100.6  658.04   110.7  653.72   115.8  653.66
   120.8  653.61   125.8  655.12   130.8  656.64   140.9  660.95     151  664.83
     161  667.42   171.1  668.74   181.2  669.04   191.2  669.12   201.3  669.45
   211.3  670.98   221.4  673.95   231.5  677.56   241.5   681.3   261.7  689.03
   271.7  692.77   281.8  696.33   291.9  699.69
#Mann= 3 , 0 , 0
       0      .1       0   115.8    .045       0   125.8      .1       0
Bank Sta=115.8,125.8
XS Rating Curve= 0 ,0
Exp/Cntr=0.3,0.1

Type RM Length L Ch R = 1 ,3708.5  ,192.8,193.1,193.4
XS GIS Cut Line= 2
     1564954.209      322384.821     1564846.763       322655.53
#Sta/Elev= 25
      10  684.92    20.1   681.9    30.1   677.8    50.2  668.34    60.3  664.53
    70.3  662.84    80.3  661.77    90.4  659.46   100.4  655.49   110.5  650.94
   115.5  649.59   120.5  648.23   125.5  648.55   130.6  648.87   140.6  652.88
   150.6  657.63   160.7  660.72   170.7  662.76   190.8  666.69   200.9  668.79
     241  677.88   251.1  680.27   271.2  685.35   281.2  688.15   291.3  691.22
#Mann= 3 , 0 , 0
       0      .1       0   115.5    .045       0   125.5      .1       0
Bank Sta=115.5,125.5
XS Rating Curve= 0 ,0
Exp/Cntr=0.3,0.1

Type RM Length L Ch R = 1 ,3515.4  ,306.8,314.3,321.7
XS GIS Cut Line= 2
     1564785.748      322311.797      1564657.51      322616.716
#Sta/Elev= 30
      10  690.29      20  684.15    30.1  678.06    40.1  672.21    50.1  667.36
    60.1  664.32    70.2  661.84    80.2   658.4    90.2  656.19   100.2   655.2
   110.3  653.68   120.3  651.62   130.3  649.35   140.3  646.82   150.4  644.61
   155.4  644.15   160.4  643.68   165.4  644.12   170.4  644.57   180.4   647.1
   190.5   650.3   220.5  659.25   230.5  662.06   240.6  664.56   250.6   666.9
   260.6  669.66   270.6  673.65   280.7  678.86   310.7  695.61   330.8  706.38
#Mann= 3 , 0 , 0
       0      .1       0   155.4    .045       0   165.4      .1       0
Bank Sta=155.4,165.4
XS Rating Curve= 0 ,0
Exp/Cntr=0.3,0.1

Type RM Length L Ch R = 1 ,3201.1  ,222.9,213.3,203.8
XS GIS Cut Line= 2
     1564574.869      322229.156     1564338.343      322474.231
#Sta/Elev= 30
      10  661.77      20  660.83    30.1  658.19    40.1  653.32    50.1  649.85
    60.1  648.34    70.1  647.38    90.2  645.99   120.2  644.35   130.2   643.9
   140.2  643.64   150.3  643.74   160.3  643.96   170.3  643.83   180.3  642.11
   190.3  639.67   195.4  639.17   200.4  638.68   205.4  639.34   210.4  640.01
   220.4  643.45   230.4  647.36   250.4  654.92   260.5  658.48   270.5  661.79
   280.5  664.67   290.5  666.95   300.5  668.44   310.5  669.39   340.6  672.04
#Mann= 3 , 0 , 0
       0     .08       0   195.4    .045       0   205.4      .1       0
Bank Sta=195.4,205.4
XS Rating Curve= 0 ,0
Exp/Cntr=0.3,0.1

Type RM Length L Ch R = 1 ,2987.8  ,400.8,395.2,389.5
XS GIS Cut Line= 2
     1564335.493      322029.676     1564210.106      322451.433
#Sta/Elev= 30
      10  644.79      20  643.88      40  642.42     110   638.1     130     637
     160  635.83     180  635.32     200  635.12     210  634.83     220  634.26
     225  634.14     230  634.02     235  634.97     240  635.91     250  641.24
     260   646.9     270  649.73     280  650.11     290  650.85     300  652.91
     310  655.67     320   658.8     340  665.45     360  672.63     370   675.2
     380     677     390  679.24     410  685.16     420  687.65     440  691.63
#Mann= 3 , 0 , 0
       0     .08       0     225    .045       0     235      .1       0
Bank Sta=225,235
XS Rating Curve= 0 ,0
Exp/Cntr=0.3,0.1

Type RM Length L Ch R = 1 ,2592.6  ,211.6,201.8,192.1
XS GIS Cut Line= 4
     1563979.279      321864.392     1563905.186      322052.473
     1563902.337      322226.306     1563899.487       322479.93
#Sta/Elev= 30
    10.1  640.43    50.5  637.84   111.2  635.43   211.8  632.93   231.1  632.66
   240.8  632.09   260.1  629.97   264.8  629.88   269.8  629.79   274.8  630.26
   279.4  630.69   289.1  632.81   298.7  636.55   308.4  642.03   318.1  648.54
     347  669.17   356.7  675.89   366.3  682.04     376   687.5   426.7  713.82
     447  723.45   457.2  728.14   467.3  732.45   487.6  740.31   497.8  744.67
   528.2  759.23   538.3  763.42   568.8  774.27   599.2  785.72   629.6  796.08
#Mann= 3 , 0 , 0
       0     .08       0   264.8    .045       0   274.8      .1       0
Bank Sta=264.8,274.8
XS Rating Curve= 0 ,0
Exp/Cntr=0.3,0.1

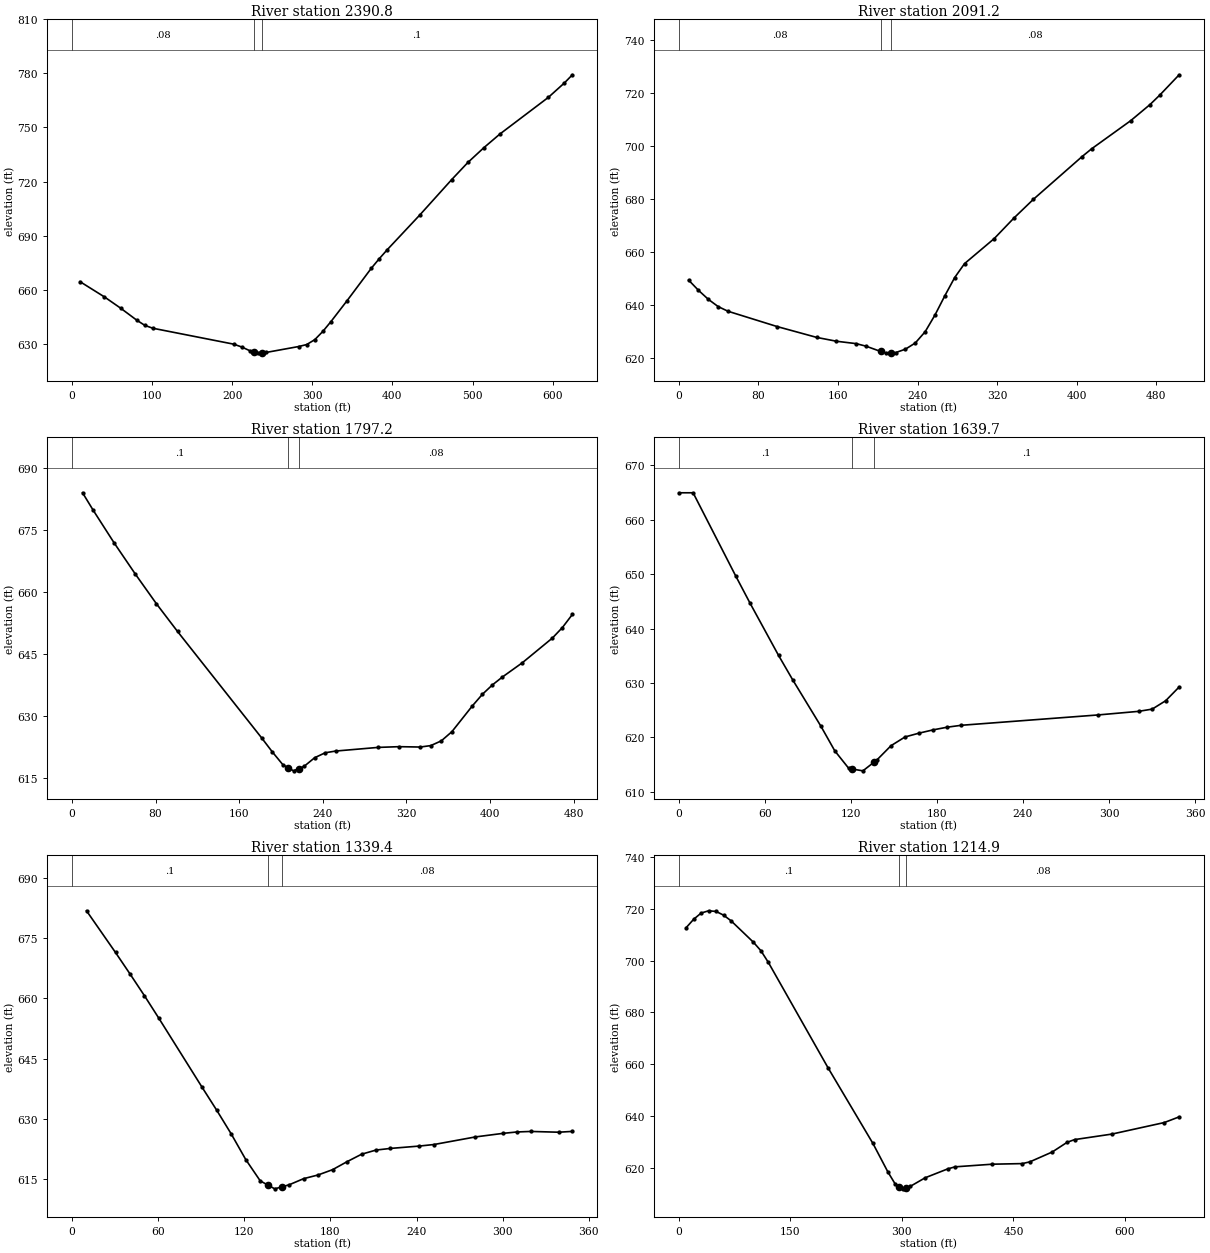
Type RM Length L Ch R = 1 ,2390.8  ,284.9,299.6,314.3
XS GIS Cut Line= 3
     1563599.268      321924.336       1563768.4      322257.653
     1563759.851      322508.427
#Sta/Elev= 30
    10.1  664.45    40.4  656.04    60.6  649.81    80.8  643.13    90.9  640.24
     101  638.64     202  629.81   212.1  628.21   222.2  626.14   227.3  625.57
   232.3  625.01   237.3  625.12   242.4  625.23   282.9   628.5     293   629.6
   303.1  632.32   313.2  636.91   323.3  642.34   343.5  653.98   373.8  671.98
   383.8   677.3   393.8   682.3     434  701.34   474.1  721.09   494.2  730.54
   514.3  738.79   534.4  746.39   594.6  766.61   614.7  774.63   624.7  779.17
#Mann= 3 , 0 , 0
       0     .08       0   227.3    .045       0   237.3      .1       0
Bank Sta=227.3,237.3
XS Rating Curve= 0 ,0
Exp/Cntr=0.3,0.1

Type RM Length L Ch R = 1 ,2091.2  ,299.8,294,288.2
XS GIS Cut Line= 3
     1563483.429      321992.629     1563394.143      322327.609
     1563412.186       322482.78
#Sta/Elev= 30
     9.9  649.39    19.8  645.55    29.7  642.15    39.6  639.41    49.5  637.65
      99  631.87   138.7  627.79   158.5  626.35   178.3  625.45   188.2  624.49
     203  622.49     208  621.98     213  622.02   217.9  622.06   227.8  623.36
   237.7  625.69   247.6  629.92   257.5  636.23   267.4  643.48   277.3  650.35
   287.2   655.6     317  665.03   336.8  672.77   356.4  679.84   405.3  695.94
     415   698.9   454.1  709.45   473.6  715.55   483.4  719.11   502.9  726.78
#Mann= 3 , 0 , 0
       0     .08       0     203    .045       0     213     .08       0
Bank Sta=203,213
XS Rating Curve= 0 ,0
Exp/Cntr=0.3,0.1

Type RM Length L Ch R = 1 ,1797.2  ,160.8,157.5,154
XS GIS Cut Line= 3
     1563147.163      321949.884     1563151.342      322323.423
     1563150.013      322428.635
#Sta/Elev= 30
    10.1  684.08    20.2  679.88    40.4   671.9    60.6  664.37    80.8  657.17
     101  650.45   181.7  624.58   191.8  621.22   201.9  618.12     207  617.39
     212  616.67     217  617.21   222.1  617.76   232.2  619.85   242.3  621.05
   252.4  621.47   292.8  622.35     313  622.53   333.2  622.44   343.3  622.79
   353.4  623.94   363.5  626.16   383.1  632.42   392.7  635.23   402.3  637.51
   411.8  639.41     431  642.89   459.7  648.87   469.2   651.4   478.8  654.59
#Mann= 3 , 0 , 0
       0      .1       0     207    .045       0     217     .08       0
Bank Sta=207,217
XS Rating Curve= 0 ,0
Exp/Cntr=0.3,0.1

Type RM Length L Ch R = 1 ,1639.7  ,303,300.3,297.7
XS GIS Cut Line= 4
     1562963.697       322043.44     1562987.762      322098.133
       1562998.7      322264.399     1563000.888      322386.912
#Sta/Elev= 24
       0  664.95      10  664.95    39.8  649.62    49.8  644.62    69.6  635.06
    79.4   630.6      99  622.11   108.8  617.53   118.6  614.29   120.9  614.19
   128.4  613.86   135.9   615.4   138.2  615.87     148  618.48   157.8  620.09
   167.6  620.79   177.4  621.39   187.2  621.88     197  622.23   292.4  624.13
   320.6  624.79   330.1   625.2   339.5  626.74   348.9  629.27
#Mann= 3 , 0 , 0
       0      .1       0   120.9    .045       0   135.9      .1       0
Bank Sta=120.9,135.9
XS Rating Curve= 0 ,0
Exp/Cntr=0.3,0.1

Type RM Length L Ch R = 1 ,1339.4  ,129,124.4,119.9
XS GIS Cut Line= 3
     1562671.261      322072.421     1562716.857      322320.346
     1562796.648      322374.491
#Sta/Elev= 29
    10.1  681.74    30.3  671.37    40.3  666.09    50.4  660.65    60.5  655.01
    90.7   637.8   100.8  632.14   110.9  626.25     121  619.89   131.1  614.58
   136.2  613.58   141.2   612.6   146.2   613.1   151.2   613.6   161.3  615.13
   171.4  616.05   181.5  617.37   191.6  619.36   201.7  621.21   211.7  622.24
   221.8  622.65     242  623.24   252.1  623.62     281  625.51   300.3   626.4
   309.9  626.74   319.6  626.87   338.9  626.68   348.5  626.88
#Mann= 3 , 0 , 0
       0      .1       0   136.2    .045       0   146.2     .08       0
Bank Sta=136.2,146.2
XS Rating Curve= 0 ,0
Exp/Cntr=0.3,0.1

Type RM Length L Ch R = 1 ,1214.9  ,1218.2,1214.9,1211.7
XS GIS Cut Line= 2
     1562454.683      321949.884     1562719.706      322568.271
#Sta/Elev= 30
      10  712.74    20.1  715.98    30.1  718.36    40.2  719.24    50.2  718.98
    60.2  717.56    70.3  715.38   100.4   707.1   110.5  703.81   120.5   699.3
   200.8   658.6   261.1  629.44   281.2  618.45   291.2  613.71   296.2  612.82
   301.2  611.94   306.2  612.41   311.3   612.9   331.4  616.22   361.5  619.62
   371.5  620.43   421.7  621.45   461.9  621.68     472  622.35   502.1  626.15
   522.2   629.9   532.2  630.94   582.4  633.07   652.7  637.51   672.8  639.71
#Mann= 3 , 0 , 0
       0      .1       0   296.2    .045       0   306.2     .08       0
Bank Sta=296.2,306.2
XS Rating Curve= 0 ,0
Exp/Cntr=0.3,0.1

Chan Stop Cuts=-1
Use User Specified Reach Order=0